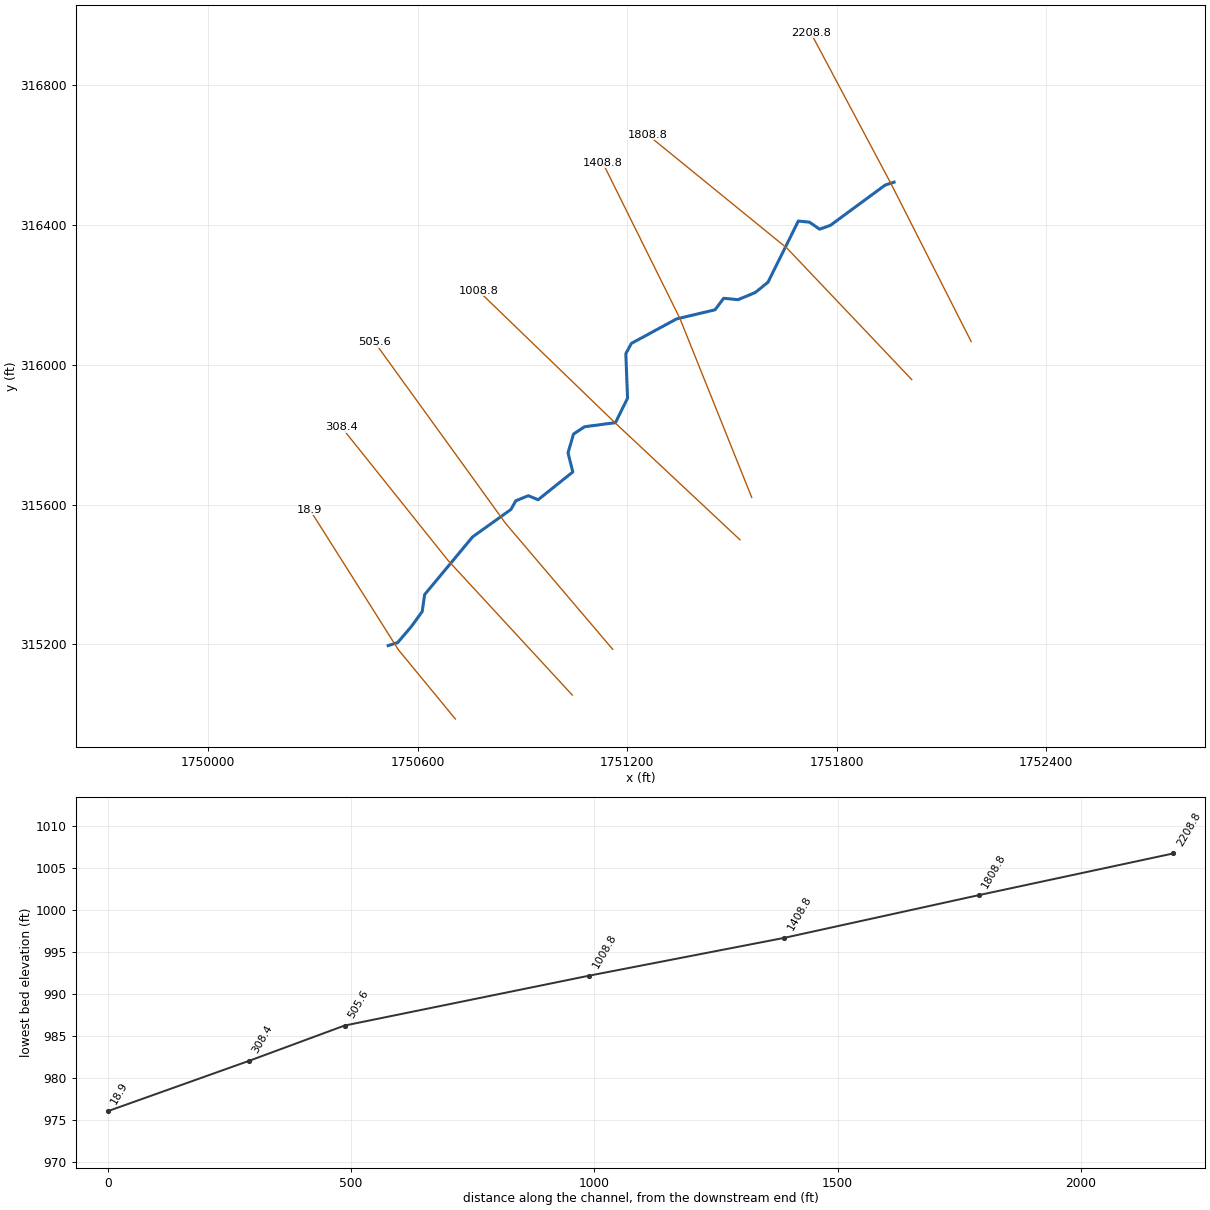
--- ShinsRnTr.prj (project) ---

Proj Title=ShinsRnTr
Current Plan=p01
Default Exp/Contr=0,0
English Units
Geom File=g01
Flow File=f01
Plan File=p01
BEGIN DESCRIPTION:
END DESCRIPTION:
DSS Export Rating Curves= 0
DSS Export Rating Curve Sorted= 0
DSS Export Volume Flow Curves= 0
DXF OffsetX= 0
DXF OffsetY= 0
DXF ScaleX= 0
DXF ScaleY= 0

--- ShinsRnTr.p01 (plan) ---

Plan Title=Floodplain
Program Version=4.00
Geom File=g01
Flow File=f01
K Sum by GR=0
Std Step Tol=0.01
Critical Tol=0.01
Num of Std Step Trials=20
Max Error Tol=0.3
Flow Tol Ratio=0.001
Split Flow NTrial=30
Split Flow Tol=0.02
Split Flow Ratio=0.02
Log Output Level=0
Friction Slope Method=1
Unsteady Friction Slope Method=2
Unsteady Bridges Friction Slope Method=1
Global Log Level=0
CheckData=False
Run HTab=0
Run UNet=0
Run PostProcess=0
UNET Theta=0
UNET Theta Warmup=0
UNET ZTol=0
UNET ZSATol=0
UNET MxIter=0
UNET MaxInSteps=0
UNET DtIC=0
UNET DtMin=0
UNET MaxCRTS=0
UNET WFStab=0
UNET SFStab=0
UNET WFX=0
UNET SFX=0
UNET DSS MLevel=0
UNET DZMax Abort=0
UNET Convert EG Bridges=0
UNET Use Existing IB Tables=0
UNET Froude Limit=0
UNET Froude Power=0
Write IC File=0
Echo Input=False
Echo Output=False
Write Detailed=0

--- ShinsRnTr.f01 (steady flow) ---

Flow Title=NFF Regression Equation
Program Version=4.00
Number of Profiles=1
Profile Names=P100yr
River Rch & RM=ShinsRnTr,Main      ,2208.8
     722
River Rch & RM=ShinsRnTr,Main      ,1808.8
730.5429
River Rch & RM=ShinsRnTr,Main      ,308.4
804.5830
River Rch & RM=ShinsRnTr,Main      ,18.9
1432.737
Boundary for River Rch & Prof#=ShinsRnTr,Main      ,1
Up Type=0
Dn Type=3
Dn Slope=0.011963

--- ShinsRnTr.g01 (geometry) ---

Geom Title=USGS 3m DEM
Program Version=4.00

River Reach=ShinsRnTr     ,Main
Reach XY= 30
     1751964.308      316523.119     1751938.731      316514.840
     1751781.981      316399.581     1751751.108      316388.578
     1751721.877      316408.589     1751690.064      316411.744
     1751603.274      316236.723     1751566.805      316207.192
     1751517.459      316186.678     1751476.335      316190.798
     1751451.715      316157.715     1751341.312      316131.539
     1751212.083      316061.479     1751196.276      316032.034
     1751201.200      315904.480     1751166.558      315834.660
     1751078.141      315822.914     1751046.513      315802.061
     1751030.765      315748.136     1751044.427      315693.580
     1750945.237      315613.962     1750917.032      315625.516
     1750881.196      315610.941     1750867.130      315585.937
     1750757.628      315507.707     1750620.196      315342.478
     1750613.359      315293.987     1750582.207      315250.933
     1750542.861      315204.806     1750515.986      315196.367

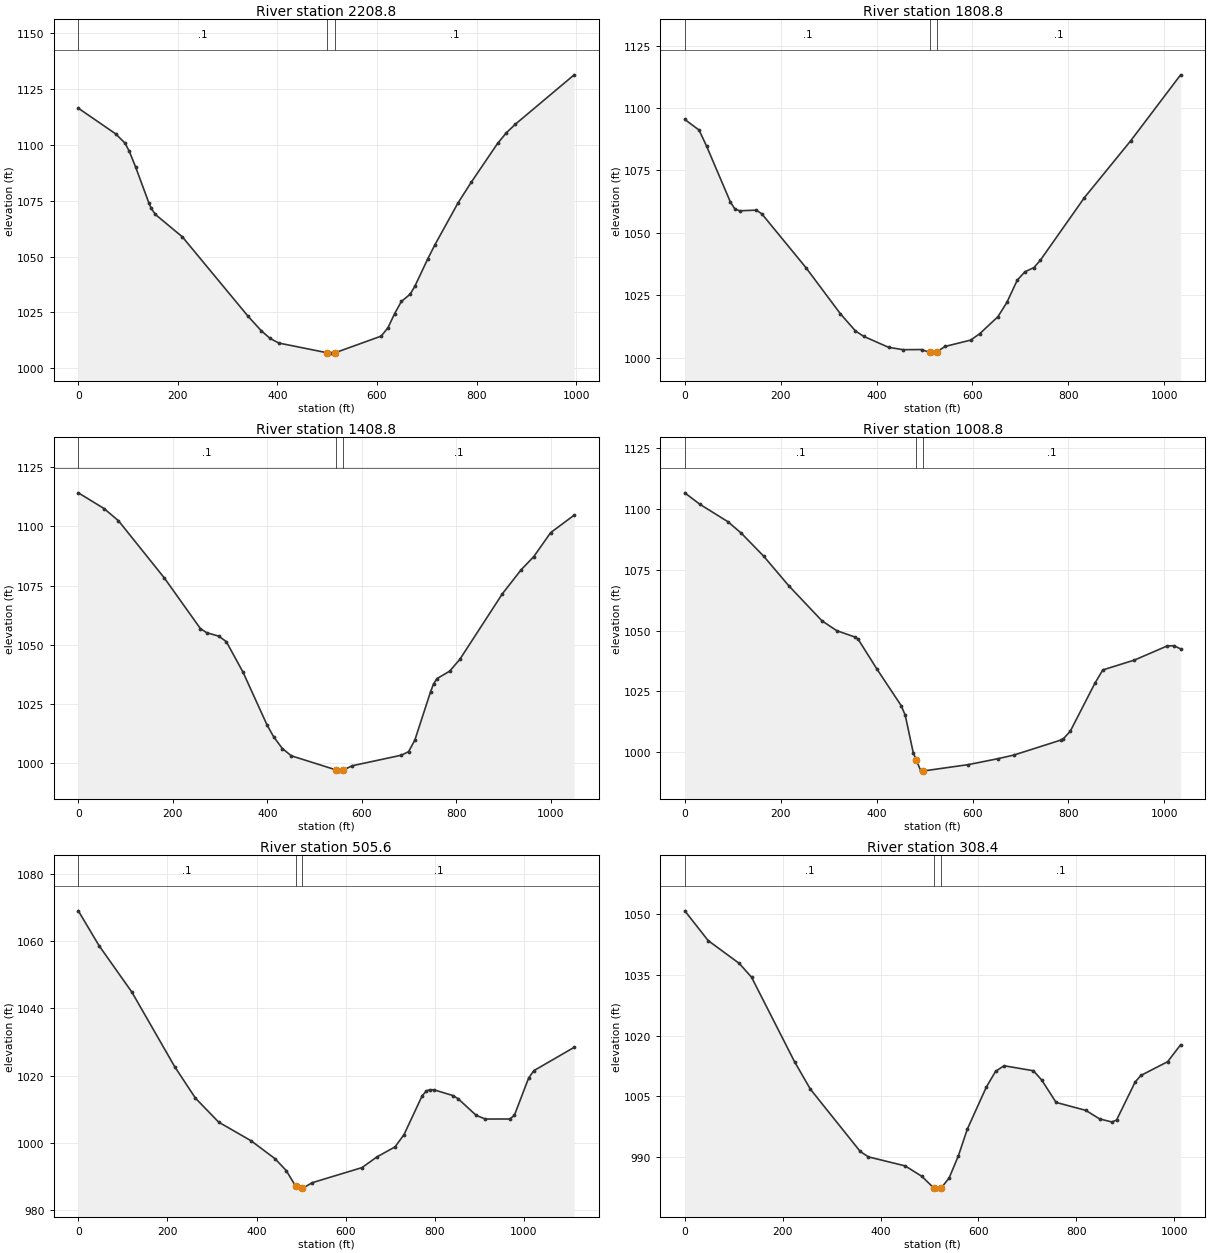
Type RM Length L Ch R = 1 ,2208.8,393.109,400,409.329
XS GIS Cut Line= 3
     1752184.808      316067.042     1751954.794      316520.039
     1751725.572      316951.040
#Sta/Elev= 30
       0 1116.44    75.0 1104.95    93.6 1100.85   102.5 1097.09   115.0 1090.17
   141.6 1074.09   146.6 1071.54   154.9 1068.84   209.0 1058.83   341.3 1023.20
   367.4 1016.82   385.1 1013.38   402.7 1011.28   500.5 1006.90   508.0 1006.76
   515.5 1006.90   608.6 1014.39   622.1 1018.15   635.5 1024.44   649.0 1029.88
   666.7 1033.16   675.9 1036.60   701.8 1048.85   716.2 1055.19   763.2 1074.15
   789.6 1083.34   842.3 1100.64   859.9 1105.42   878.1 1109.27   996.2 1131.38
#Mann= 3 , 0 , 0
       0     0.1       0   500.5   0.045       0   515.5     0.1       0
Bank Sta=   500.5,   515.5
Exp/Cntr=0.3,0.1

Type RM Length L Ch R = 1 ,1808.8,407.305,400,391.143
XS GIS Cut Line= 3
     1752014.746      315958.002     1751657.878      316333.960
     1751257.941      316659.544
#Sta/Elev= 30
       0 1095.46    29.8 1091.20    45.6 1084.70    95.2 1062.31   104.7 1059.53
   114.6 1058.84   149.1 1059.11   160.7 1057.61   252.6 1036.07   324.4 1017.59
   356.0 1010.65   373.3 1008.49   425.0 1004.11   455.4 1003.16   494.0 1003.22
   510.9 1002.04   516.2 1001.78   525.9 1002.33   542.7 1004.45   596.5 1007.02
   615.3 1009.61   652.9 1016.35   671.7 1022.09   693.4 1031.05   709.3 1034.38
   728.1 1036.07   741.7 1039.07   833.5 1064.15   929.7 1086.84  1034.1 1113.35
#Mann= 3 , 0 , 0
       0     0.1       0   510.9   0.045       0   525.9     0.1       0
Bank Sta=   510.9,   525.9
Exp/Cntr=0.3,0.1

Type RM Length L Ch R = 1 ,1408.8,389.405,400,408.67
XS GIS Cut Line= 3
     1751556.724      315620.475     1751350.835      316133.434
     1751130.138      316578.591
#Sta/Elev= 30
       0 1114.19    54.3 1107.57    85.0 1102.40   182.3 1078.18   258.5 1056.84
   271.8 1055.12   297.4 1053.67   313.3 1051.34   348.6 1038.47   399.8 1016.04
   413.7 1011.12   431.9 1006.22   450.9 1003.15   545.2  997.22   552.7  996.68
   560.2  997.11   579.8  998.95   683.6 1003.40   699.1 1004.90   712.3 1009.76
   745.6 1030.17   752.1 1033.57   759.2 1035.74   786.0 1038.89   807.6 1043.88
   897.8 1071.61   937.6 1081.76   964.1 1087.26   999.8 1097.37  1049.6 1104.77
#Mann= 3 , 0 , 0
       0     0.1       0   545.2   0.045       0   560.2     0.1       0
Bank Sta=   545.2,   560.2
Exp/Cntr=0.3,0.1

Type RM Length L Ch R = 1 ,1008.8,509.713,503.156,495.363
XS GIS Cut Line= 3
     1751523.151      315499.222     1751165.426      315834.268
     1750774.422      316211.972
#Sta/Elev= 30
       0 1106.75    31.1 1102.08    89.9 1094.86   117.8 1090.14   164.3 1080.71
   216.4 1068.58   285.9 1054.08   316.7 1050.01   355.4 1047.35   361.8 1046.37
   400.7 1034.17   451.1 1019.17   459.6 1015.20   476.3  999.80   482.6  996.71
   491.9  992.39   494.2  992.18   497.6  992.25   591.0  994.86   652.6  997.29
   686.2  998.80   784.7 1005.01   789.1 1005.46   803.7 1008.60   855.1 1028.38
   871.6 1033.85   937.6 1037.91  1005.2 1043.67  1020.2 1043.82  1033.8 1042.48
#Mann= 3 , 0 , 0
       0     0.1       0   482.6   0.045       0   497.6     0.1       0
Bank Sta=   482.6,   497.6
Exp/Cntr=0.3,0.1

Type RM Length L Ch R = 1 ,505.6,194.552,197.162,198.756
XS GIS Cut Line= 3
     1751158.758      315185.711     1750851.867      315546.472
     1750477.311      316064.779
#Sta/Elev= 30
       0 1069.08    46.7 1058.67   120.0 1044.92   216.1 1022.72   262.9 1013.30
   315.1 1006.16   387.6 1000.63   441.5  995.28   466.7  991.74   487.9  987.07
   500.7  986.22   502.9  986.41   524.6  988.12   636.7  992.63   670.2  995.81
   710.8  998.80   731.0 1002.45   771.6 1013.98   781.3 1015.46   788.3 1015.80
   798.3 1015.79   840.8 1014.08   852.7 1013.11   893.2 1008.17   913.5 1007.09
   968.4 1007.10   978.7 1008.19  1010.9 1019.36  1022.7 1021.51  1112.9 1028.44
#Mann= 3 , 0 , 0
       0     0.1       0   487.9   0.045       0   502.9     0.1       0
Bank Sta=   487.9,   502.9
Exp/Cntr=0.3,0.1

Type RM Length L Ch R = 1 ,308.4,293.713,289.514,286.056
XS GIS Cut Line= 3
     1751042.912      315054.873     1750686.894      315440.678
     1750381.908      315822.184
#Sta/Elev= 30
       0 1050.90    47.7 1043.54   111.3 1037.88   136.4 1034.47   224.3 1013.54
   256.7 1006.74   358.6  991.31   375.4  989.97   450.5  987.74   484.6  985.15
   509.4  982.21   515.1  981.99   524.4  982.33   540.3  984.77   559.3  990.28
   577.3  996.81   616.3 1007.26   635.3 1011.17   652.5 1012.54   712.5 1011.30
   729.4 1009.02   758.9 1003.46   819.7 1001.49   847.6  999.39   873.0  998.61
   882.5  999.11   920.5 1008.53   932.1 1010.13   986.9 1013.55  1013.4 1017.74
#Mann= 3 , 0 , 0
       0     0.1       0   509.4   0.045       0   524.4     0.1       0
Bank Sta=   509.4,   524.4
Exp/Cntr=0.3,0.1

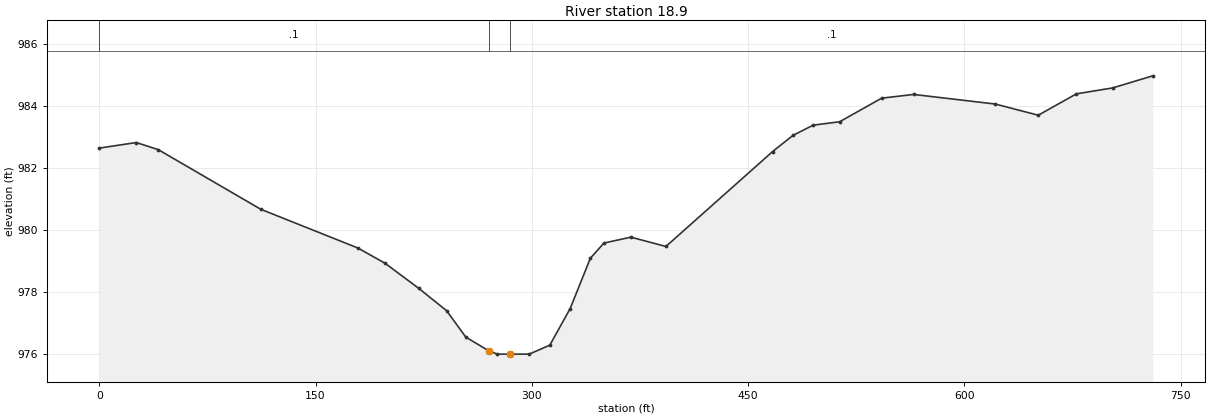
Type RM Length L Ch R = 1 ,18.9,25.226,18.922,12.952
XS GIS Cut Line= 3
     1750708.296      314986.230     1750545.153      315184.453
     1750291.957      315585.040
#Sta/Elev= 30
       0  982.64    25.7  982.82    41.0  982.59   112.0  980.67   179.4  979.42
   198.2  978.93   221.6  978.12   240.9  977.40   254.2  976.55     270  976.11
   276.0  976.00     285  976.00   298.2  976.00   312.5  976.29   326.6  977.47
   340.6  979.09   350.0  979.58   368.7  979.77   393.0  979.47   467.0  982.53
   481.1  983.05   495.1  983.38   513.5  983.49   542.6  984.25   564.8  984.37
   621.5  984.06   651.2  983.70   677.7  984.39   702.8  984.58   730.6  984.97
#Mann= 3 , 0 , 0
       0     0.1       0     270   0.045       0     285     0.1       0
Bank Sta=     270,     285
Exp/Cntr=0.3,0.1